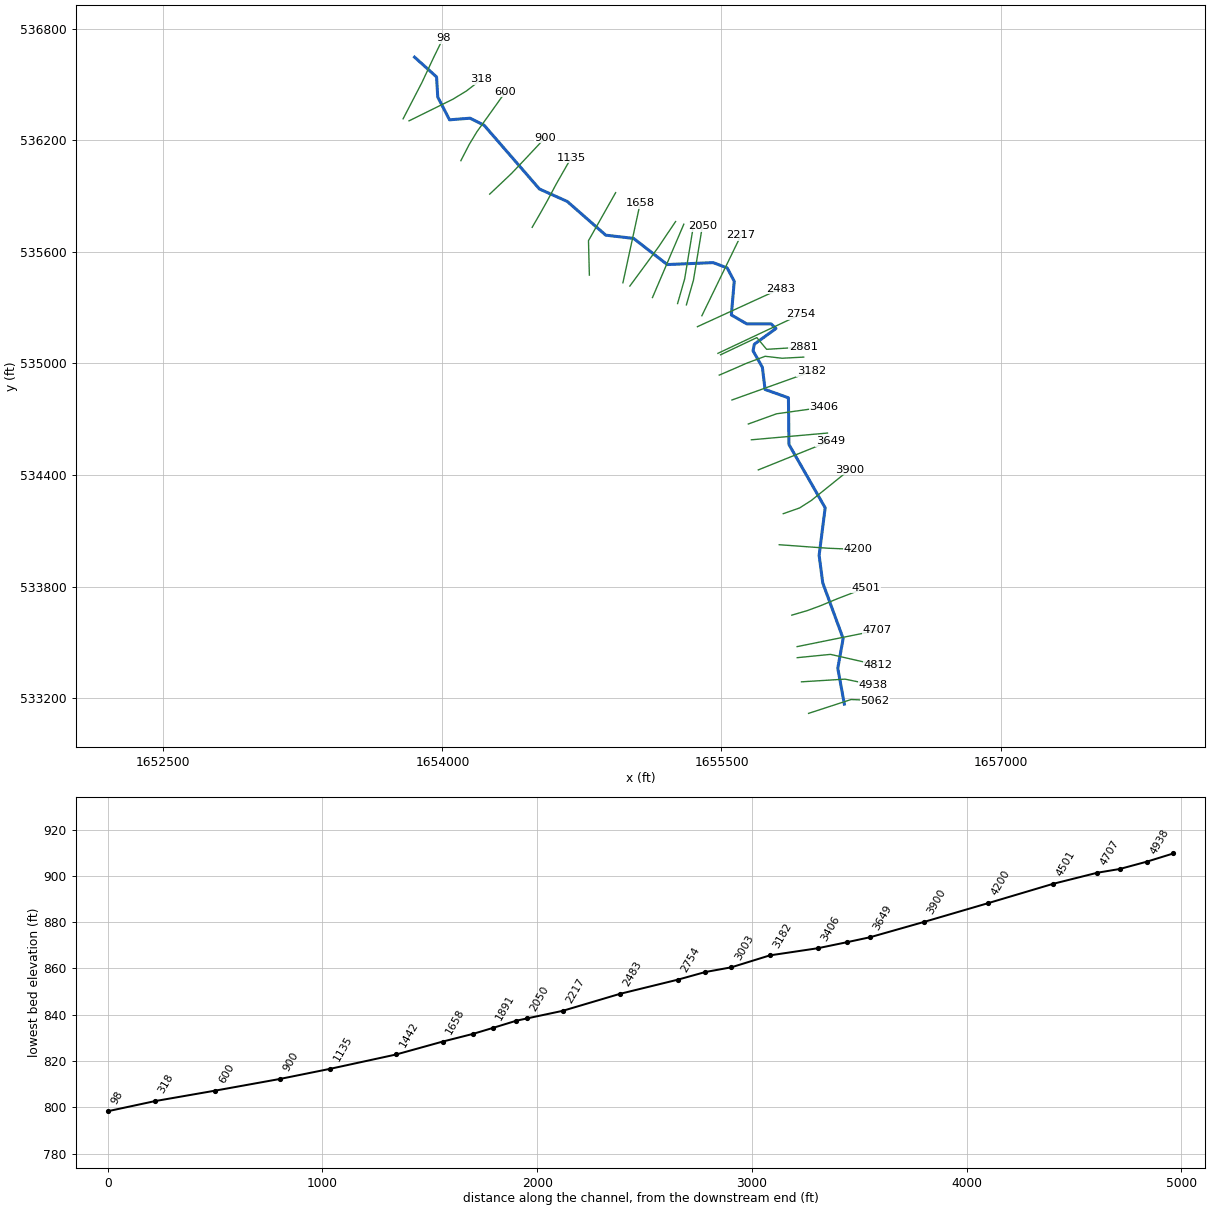
--- BigRnII.prj (project) ---

Proj Title=BigRnII
Current Plan=p01
Default Exp/Contr=0,0
English Units
Geom File=g01
Flow File=f01
Plan File=p01
BEGIN DESCRIPTION:
---------- MODELED AS PART OF WVEM CTP PROGRAM, 2025----------
Stream Name: Big Run II
Flood Zone: AFH
Marshall County, WV
HEC-RAS Version: RAS 6.6
Vertical Datum: NAVD88
Projection: NAD 1983 StatePlane West Virginia N FIPS 4701 (US Feet)
Terrain: 1-meter West Virginia FEMA R3 South Central (collected 2018-2019)
Land Use: 2024 NLCD
Hydrologic Method:
Duda et al., "Estimation of magnitude and frequency of floods for rural, unregulated streams in and near Virginia and West Virginia." September 8, 2025.
Additional Model Notes:
None
END DESCRIPTION:
DSS File=dss
DSS Export Rating Curves= 0
DSS Export Rating Curve Sorted= 0
DSS Export Volume Flow Curves= 0
DXF OffsetX= 0
DXF OffsetY= 0
DXF ScaleX= 0
DXF ScaleY= 0

--- BigRnII.p01 (plan) ---

Plan Title=Floodplain
Program Version=6.60
Short Identifier=Floodplain
Geom File=g01
Flow File=f01
Subcritical Flow
K Sum by GR= 0
Std Step Tol= 0.01
Critical Tol= 0.01
Num of Std Step Trials= 20
Max Error Tol= 0.3
Flow Tol Ratio= 0.001
Split Flow NTrial= 30
Split Flow Tol= 0.02
Split Flow Ratio= 0.02
Log Output Level= 0
Friction Slope Method= 1
Unsteady Friction Slope Method= 2
Unsteady Bridges Friction Slope Method= 1
Parabolic Critical Depth
Global Vel Dist= 0 , 0 , 0
Global Log Level= 0
CheckData=False
Encroach Param=-1 ,0,0, 0
Flow Ratio Tolerance=0.1
Flow Ratio Min Ratio=0.5
Flow Ratio Max Ratio=4
Flow Ratio Max Iterations= 10
Computation Interval=0.1SEC
Output Interval=1SEC
Instantaneous Interval=Max Profile
Mapping Interval=1HOUR
Computation Time Step Use Courant=        0
Computation Time Step Use Time Series=    0
Computation Time Step Count To Double=0
Computation Time Step Max Doubling=0
Computation Time Step Max Halving=0
Computation Time Step Residence Courant=0
Run HTab= 0
Run UNet= 0
Run Sediment= 0
Run PostProcess= 0
Run WQNet= 0
Run RASMapper=-1
UNET Theta= 0
UNET Theta Warmup= 0
UNET ZTol= 0
UNET ZSATol= 0
UNET MxIter= 0
UNET Max Iter WO Improvement= 0
UNET MaxInSteps= 0
UNET DtIC= 0
UNET DtMin= 0
UNET MaxCRTS= 0
UNET WFStab= 0
UNET SFStab= 0
UNET WFX= 1
UNET SFX= 1
UNET Gravity=32.17405
UNET 1D Methodology=Finite Difference
UNET DSS MLevel= 1
UNET Pardiso=0
UNET DZMax Abort= 0
UNET Use Existing IB Tables= 0
UNET Froude Reduction=False
UNET Froude Limit= 0
UNET Froude Power= 0
UNET D1 Cores= 0
UNET WindReference=Eulerian
UNET WindDragFormulation=Hsu (1988)
UNET D2 Coriolis=0
UNET D2 Cores= 0
UNET D2 Theta= 1
UNET D2 Theta Warmup= 1
UNET D2 Z Tol= 0.01
UNET D2 Volume Tol= 0.01
UNET D2 Max Iterations= 20
UNET D2 Advanced Convergence=0
UNET D2 WS Max Tol=0.15
UNET D2 WS RMS Tol=0.002
UNET D2 WS Stall Tol=1
UNET D2 Equation= 0
UNET D2 RampUpFraction=0.1
UNET D2 TimeSlices= 1
UNET D2 Turbulence Formulation=Non-Conservative (original)
UNET D2 Eddy Viscosity=0.3
UNET D2 Transverse Eddy Viscosity=0.1
UNET D2 Smagorinsky Mixing=0
UNET D2 BCVolumeCheck=0
UNET D2 Cores=0
UNET D2 SolverType=PARDISO (Direct)
UNET D2 Minimum Iterations= 3
UNET D2 Maximum Iterations= 30
UNET D2 Restart Number= 10
UNET D2 Relaxation Coeff=1.3
UNET D2 SOR Precondition Iterations= 10
UNET D2 ILUT Maximum Fill= 8
UNET D2 ILUT Tolerance=1E-08
UNET D2 Convergence Tolerance=0.00001
PS Theta= 1
PS WS Tol= 0.01
PS Volume Tol= 0.01
PS Max Iterations= 20
PS Equation= 0
PS Advance Time Step=-1
PS Target Courant=0.9
PS Time Slices= 1
PS Iterate With 2D=0
PS Project Initial WSE from DS=-1
PS Ramp Up Initial WSE from US=-1
PS Cores=0
UNET D1D2 MaxIter= 0
UNET D1D2 ZTol=0.01
UNET D1D2 QTol=0.1
UNET D1D2 MinQTol=1
DSS File=dss
Write IC File= 0
Write IC File at Fixed DateTime=0
Write IC File at Sim End=0
Echo Input=False
Echo Parameters=False
Echo Output=False
Write Detailed= 0
HDF Write Warmup=0
HDF Write Time Slices=0
HDF Flush=0
HDF Compression= 1
HDF Chunk Size= 1
HDF Spatial Parts= 1
HDF Use Max Rows=0
HDF Fixed Rows= 1
Calibration Method= 0
Calibration Iterations= 20
Calibration Max Change=0.05
Calibration Tolerance=0.2
Calibration Maximum=1.5
Calibration Minimum=0.5
Calibration Optimization Method= 1
WQ AD Non Conservative
WQ ULTIMATE=-1
WQ Max Comp Step=1HOUR
WQ Output Interval=15MIN
WQ Output Selected Increments= 0
WQ Create Restart=0
WQ Fixed Restart=0
WQ System Summary=0
WQ Write To DSS=0
Sorting and Armoring Iterations= 10
XS Update Threshold= 0.02
Bed Roughness Predictor= 0
Processes Affected by Predictor=Sediment Only
Hydraulics Update Threshold= 0.02
Energy Slope Method= 1
Volume Change Method= 1
Sediment Retention Method= 0
Sediment TS Multiplier= 1
Warm Up Method= 0
XS Weighting Method= 0
Number of US Weighted Cross Sections= 1
Number of DS Weighted Cross Sections= 1
Upstream XS Weight=0
Main XS Weight=1
Downstream XS Weight=0
Number of DS XS's Weighted with US Boundary= 1
Upstream Boundary Weight= 1
Weight of XSs Associated with US Boundary= 0
Number of US XS's Weighted with DS Boundary= 1
Downstream Boundary Weight= 0.5
Weight of XSs Associated with DS Boundary= 0.5
Percentile Method= 0
Sediment Output Level= 3
Mass or Volume Output= 0
Output Increment Type= 1
Profile and TS Output Increment= 1
Transport Output Increment 1
XS Output Flag= 0
XS Output Increment= 10
Read HDF5 Sediment Hotstart= 0
Sediment Hotstart Type= 0
Write Gradation File= 0
Read Gradation Hotstart= 0
Write HDF5 File= 1
Write Binary Output= 1
Write DSS Sediment File= 0
DSS Sediment Output Type= 1
SV Curve= 0
Specific Gage Flag= 0
Subcell Erosion Methods= 0
Subcell Deposition Methods= 0
Advection Scheme= 1
Matrix Solver= 0
Implicit Weighting Factor= 1
Maximum Outer Loop Convergence Iterations= 5
Convergence Maximum Absolute= 0.001
Convergence RMSE= 0.0001
Grain Fractions Max Abs Error= 0.001
Max Subgrid Regions= 1
Max Subgrid Length Scale= 3.402823E+38
Initial Layer Thickness= 3
Min Layer Thickness= 0.1
Max Layer Thickness= 6
Number of Layers= 5

--- BigRnII.f01 (steady flow) ---

Flow Title=Flow
Program Version=6.60
Number of Profiles= 2
Profile Names=P100yr,Banks
River Rch & RM=BigRnII,Main,5062
     806    40.3
River Rch & RM=BigRnII,Main,1442
    1050    52.5
Boundary for River Rch & Prof#=BigRnII,Main            , 1
Up Type= 0
Dn Type= 3
Dn Slope=0.024774
DSS Import GetInterval= 0
DSS Import GetPeak= 0
DSS Import FillOption= 0

--- BigRnII.g01 (geometry) ---

Geom Title=Geometry
Program Version=6.60

River Reach=BigRnII         ,Main
Reach XY= 30
1656160.31980207533168.8560113311656125.06618245533361.060677215
     1656153.909      533521.218     1656044.272      533819.952
     1656024.809      533968.416     1656057.308      534223.828
     1655862.639      534563.918     1655859.742      534815.076
     1655734.146      534859.838     1655719.708      534979.026
     1655669.562      535067.805     1655676.325      535102.814
     1655792.887       535187.55     1655766.233      535212.613
     1655636.145      535212.215        1655553.      535260.352
     1655568.515      535441.361     1655530.722      535512.969
     1655455.534      535541.612     1655208.486      535531.268
     1655027.477        535671.7     1654877.896      535689.204
     1654670.978      535870.362     1654521.173      535937.495
      1654224.05      536279.995     1654148.215      536317.913
     1654038.192       536309.21     1653974.839       536431.54
     1653968.474      536539.748     1653850.073      536646.113

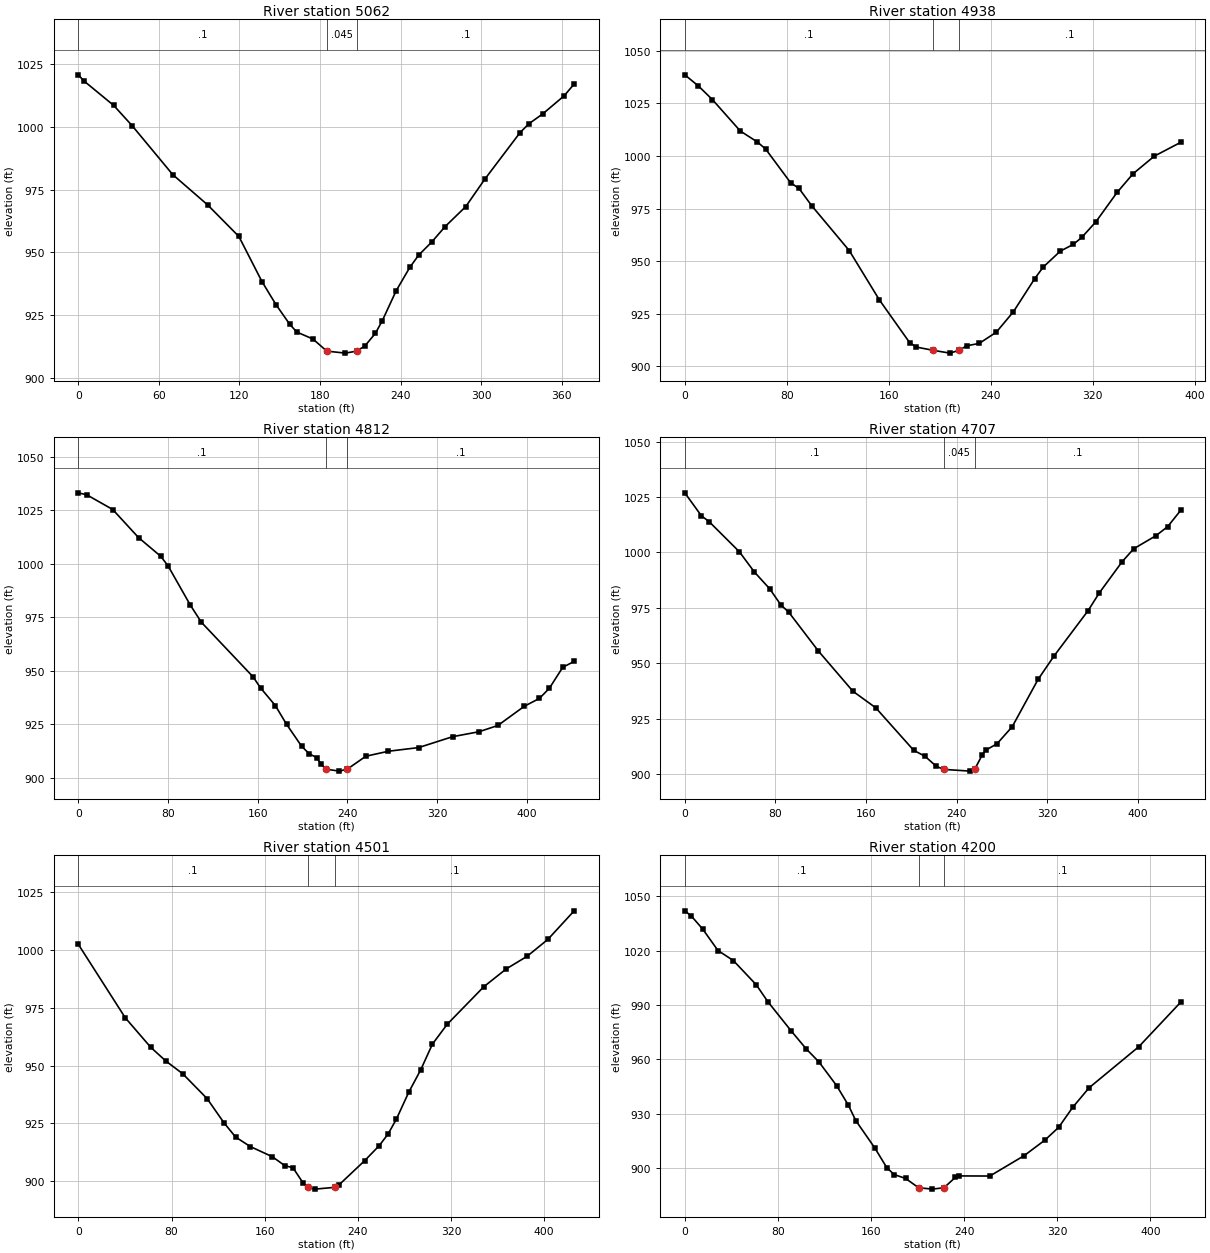
Type RM Length L Ch R = 1 ,5062    ,126.4,123.6,121
XS GIS Cut Line= 3
1655968.16879466533118.7389934821656196.75390819533193.324277005
1656325.53425384533187.421844496
#Sta/Elev= 30
       0 1020.74     4.1 1018.33    26.4 1008.51    40.2 1000.38    70.3  980.96
    96.4  968.83   119.6  956.27   136.8  938.28   147.2  929.12   157.5  921.24
   162.7  918.18   174.8  915.36   185.1  910.55   198.9  909.75  207.23  910.54
   213.4  912.56   221.3  917.65   226.5  922.75   236.8  934.66   246.9  943.92
   253.5  948.82   263.3  954.08   273.2   960.2   288.6  968.19   302.8  979.12
     329  997.66   335.6 1001.21   345.9 1005.14   361.9 1012.37369.3612 1017.07
#Mann= 3 ,-1,0
       0      .1       0   185.1    .045       0  207.23      .1       0
Bank Sta=185.1,207.23
XS Rating Curve= 0 ,0
Exp/Cntr(USF)=0,0
Exp/Cntr=0.3,0.1

Type RM Length L Ch R = 1 ,4938    ,128.8,126.2,123.4
XS GIS Cut Line= 3
1655930.07127574533288.299781922  1656164.022237533302.787570808
1656315.33914314533271.665653942
#Sta/Elev= 30
       0  1038.6    10.7 1033.28    21.6 1026.84    43.6 1011.83    56.7 1006.74
    63.3 1003.37      83  987.26    89.6  984.53    99.5  976.35     129  954.96
   152.6  931.52   176.3  911.23   181.6  909.07   194.7  907.54   207.9  906.19
  215.12  907.52   221.1  909.68   230.9  910.81   244.3  916.14   257.7  925.84
   274.4  941.59   281.1  947.12   294.5  954.71   304.6  957.89   311.3  961.21
   322.4  968.65     339  982.62   351.5  991.49   368.2  999.89388.8834 1006.46
#Mann= 3 ,-1,0
       0      .1       0   194.7    .045       0  215.12      .1       0
Bank Sta=194.7,215.12
XS Rating Curve= 0 ,0
Exp/Cntr(USF)=0,0
Exp/Cntr=0.3,0.1

Type RM Length L Ch R = 1 ,4812    ,96.7,105,107.2
XS GIS Cut Line= 5
1655906.97815786533418.0846673171656085.81157726 533435.87468998
 1656183.3126946 533413.658527061656256.43820451533396.996486886
1656341.75168218533377.557549386
#Sta/Elev= 30
       0 1033.08     7.6 1032.14    30.7 1025.27    53.7 1012.16    73.5 1003.42
    80.1  998.87    99.9  980.59   109.8  972.55   155.9  947.05   162.5  941.92
   175.7  933.66   185.7  924.91   199.2  914.61   205.9  911.13   212.7  909.31
     216  906.49  220.92 903.929   232.8  903.02  239.86 903.928   256.4  909.98
   276.6  912.32   303.5  914.02   333.8  919.12   357.3  921.42   374.2  924.36
   397.7  933.32   411.2  936.99   420.1  941.75     432  951.53   442.2  954.29
#Mann= 3 ,-1,0
       0      .1       0  220.92    .045       0  239.86      .1       0
Bank Sta=220.92,239.86
XS Rating Curve= 0 ,0
Exp/Cntr(USF)=0,0
Exp/Cntr=0.3,0.1

Type RM Length L Ch R = 1 ,4707    ,201.1,206.1,206.8
XS GIS Cut Line= 2
1655906.68195082533477.5895187531656335.89870361533564.317852307
#Sta/Elev= 30
       0 1026.87    14.7 1016.49    21.4 1013.92    48.2 1000.29    61.5  991.14
    74.9  983.65      85  976.22    91.7  973.12     118  955.53   148.4  937.44
   168.7  929.92   202.1   910.8   212.2  908.06   222.2  903.52   228.9  902.16
   252.3  901.39  255.96  902.16   262.8  908.79   265.7   910.8   275.8  913.75
   289.2  921.45     312  942.75     326  953.24   356.1   973.7   366.1  981.76
   386.2  995.78   396.5 1001.66     416 1007.51   426.4  1011.6   437.9 1018.93
#Mann= 3 ,-1,0
       0      .1       0   228.9    .045       0  255.96      .1       0
Bank Sta=228.9,255.96
XS Rating Curve= 0 ,0
Exp/Cntr(USF)=0,0
Exp/Cntr=0.3,0.1

Type RM Length L Ch R = 1 ,4501    ,307.2,301.3,296.9
XS GIS Cut Line= 6
1655877.82492326533646.6715212611655961.99240585533671.428689584
1656032.39777684533697.399766251  1656124.799823533735.695621416
1656194.96634933533762.6903180931656276.86054251533794.066895753
#Sta/Elev= 30
       0 1002.48    40.3  970.71    62.2  957.92    75.2  951.98    89.6  946.51
   110.6  935.72   124.9  925.38     135  919.12   147.6  915.02   166.6   910.6
   177.2  906.77   184.3  905.82   193.1  899.15  196.86897.3556   203.1  896.59
  220.01897.3548   223.4  898.24   245.8  908.88   258.4  915.43     266  920.49
     273  926.79   283.7  938.53   293.9  948.13     304  959.31   316.7   967.9
   348.1  984.13   367.5  991.89   385.3  997.31   403.1  1004.6   425.7 1016.98
#Mann= 3 ,-1,0
       0      .1       0  196.86    .045       0  220.01      .1       0
Bank Sta=196.86,220.01
XS Rating Curve= 0 ,0
Exp/Cntr(USF)=0,0
Exp/Cntr=0.3,0.1

Type RM Length L Ch R = 1 ,4200    ,291.8,299.8,309.8
XS GIS Cut Line= 6
1655810.62591067 534025.332181261655897.89049992534018.915527418
1655972.68857868534013.4152103361656072.44494084534006.430316165
1656147.57274334 534003.302041591656235.81600517 534001.03104876
#Sta/Elev= 30
       0 1041.91     5.5 1039.12    15.4 1031.82    28.5    1020    41.7 1014.46
    61.4 1001.08    71.3   991.8    91.3   975.7   104.2  965.78   115.3  958.45
   130.5  945.34   140.4  934.77   146.9  926.13   163.4  910.85   173.5  900.17
   179.8  896.33   189.7  894.17  200.83889.0516   212.7  888.27  222.71889.0504
   232.5   894.8   235.7  895.56   262.1   895.5   291.6  906.77   309.4  915.34
   321.2  922.37   333.3  933.44   347.4  944.24   390.1  966.91     426  991.42
#Mann= 3 ,-1,0
       0      .1       0  200.83    .045       0  222.71      .1       0
Bank Sta=200.83,222.71
XS Rating Curve= 0 ,0
Exp/Cntr(USF)=0,0
Exp/Cntr=0.3,0.1

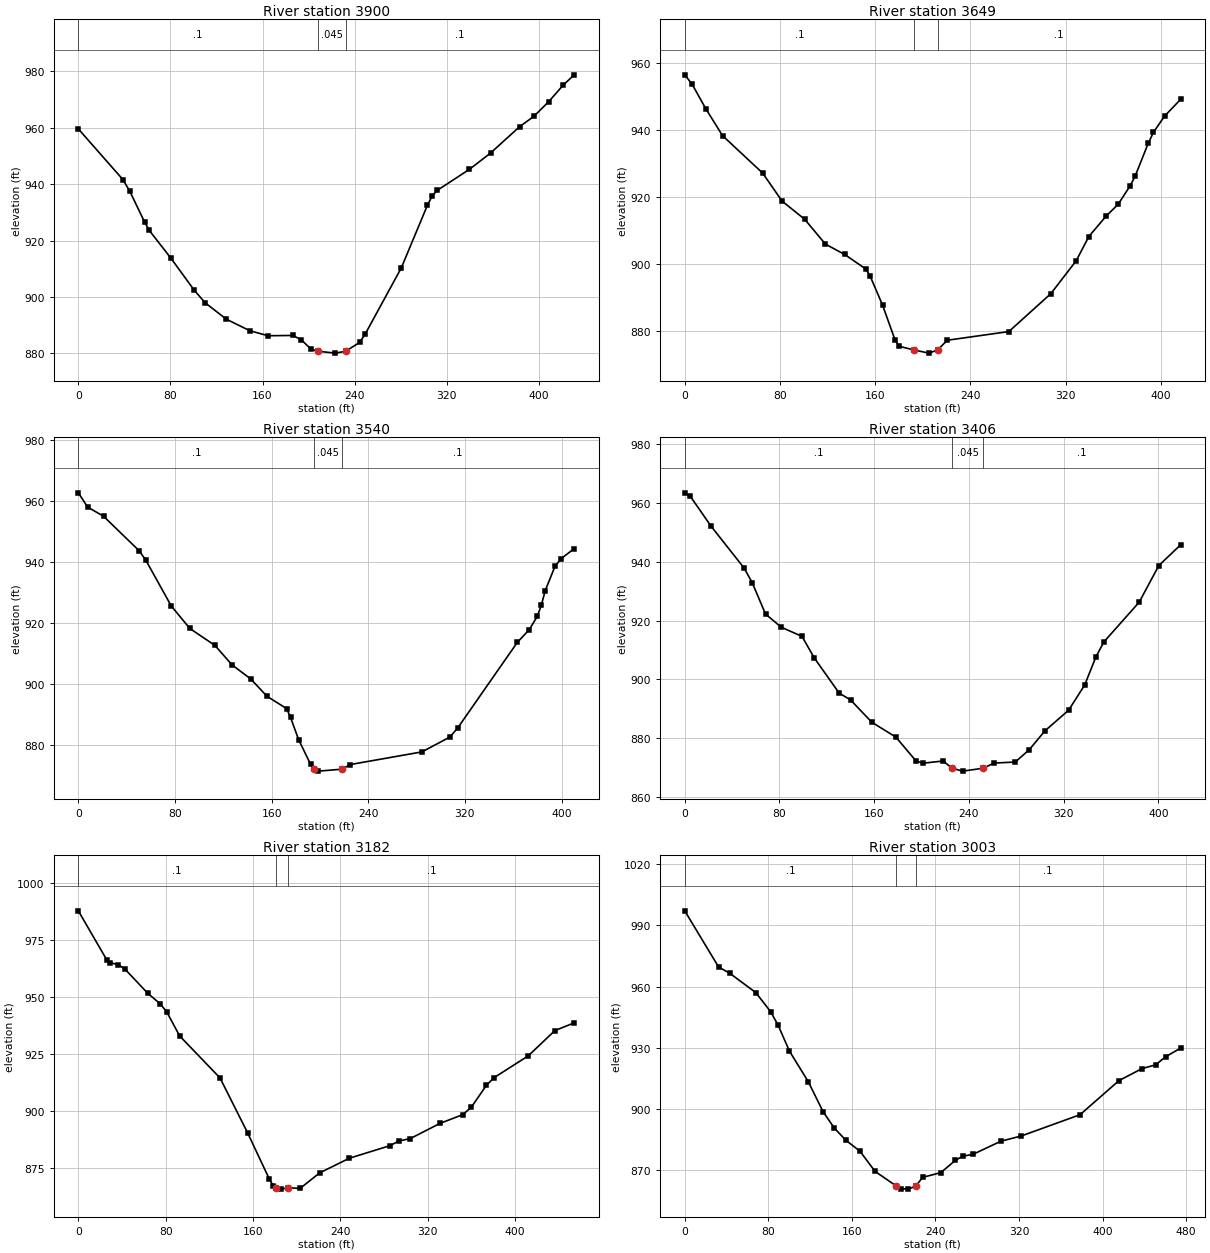
Type RM Length L Ch R = 1 ,3900    ,253.5,250.8,247.3
XS GIS Cut Line= 6
1655832.03531668534192.1294198331655919.77168976534222.921353012
1655983.24564417534263.4839359221656061.12081651534326.217078179
1656119.52686767 534373.267180921656187.66813558534428.158475339
#Sta/Elev= 30
       0  959.54    38.7   941.6    44.7  937.46    57.5   926.6    61.5  923.67
    80.5   913.7   100.6  902.45   110.1  897.98   128.5  892.16     149  888.05
   164.8  886.28   186.4  886.38   193.8  884.81   202.2  881.52  208.17880.7896
   223.3  880.12  232.26880.7896   244.4  883.92   249.2  886.86   280.6  910.34
   303.3  932.53   307.6  935.94   311.8  937.77   339.8  945.23   358.1  950.99
   383.4  960.35   395.6  963.94   408.7  969.22   421.3  975.09   430.8   978.7
#Mann= 3 ,-1,0
       0      .1       0  208.17    .045       0  232.26      .1       0
Bank Sta=208.17,232.26
XS Rating Curve= 0 ,0
Exp/Cntr(USF)=0,0
Exp/Cntr=0.3,0.1

Type RM Length L Ch R = 1 ,3649    ,111,109,104.5
XS GIS Cut Line= 2
1655698.02737213534427.5345864691656084.49286762534583.120557903
#Sta/Elev= 30
       0  956.51     6.2   953.7    17.6  946.45    31.8  938.35    65.5  927.19
    81.8  918.84   100.7  913.45   118.2  906.02   134.3  902.94     152  898.63
   155.6  896.61   166.2  887.82   176.8  877.32   180.3  875.54  192.53874.4602
   205.1  873.51  212.56874.4594   220.5  877.35   272.3  879.94   307.6  891.26
   328.9  901.07   339.5  908.29   354.1  914.41   364.2  917.94   374.3  923.48
   378.4  926.31   389.4  936.09   393.8  939.38   403.1  944.19   416.6   949.2
#Mann= 3 ,-1,0
       0      .1       0  192.53    .045       0  212.56      .1       0
Bank Sta=192.53,212.56
XS Rating Curve= 0 ,0
Exp/Cntr(USF)=0,0
Exp/Cntr=0.3,0.1

Type RM Length L Ch R = 1 ,3540    ,132.2,134.2,133.9
XS GIS Cut Line= 2
1655660.76290032 534589.274565641656069.62504422534625.558868454
#Sta/Elev= 30
       0   962.8     7.7  958.12    20.9  955.09    50.5   943.7      56  940.57
    76.9  925.63    92.3  918.22   113.1  912.64   127.2  906.27   142.8   901.6
   156.1  895.96   172.4  891.89   175.7  888.98   182.3  881.73   192.2  873.62
  195.26871.9695   198.8  871.34  218.08871.9704   225.1   873.5   284.4  877.66
   307.5  882.52     314   885.5   363.4  913.65   373.3  917.84   379.9  922.19
   383.2  925.79   386.5  930.66   394.6  938.66   399.7  941.19   410.5  944.46
#Mann= 3 ,-1,0
       0      .1       0  195.26    .045       0  218.08      .1       0
Bank Sta=195.26,218.08
XS Rating Curve= 0 ,0
Exp/Cntr(USF)=0,0
Exp/Cntr=0.3,0.1

Type RM Length L Ch R = 1 ,3406    ,213.7,223.9,227.6
XS GIS Cut Line= 3
1655644.25869069534674.2813541351655796.16529862534729.101878921
1656050.88275351534764.668259829
#Sta/Elev= 30
       0  963.49     4.8  962.25    22.2  952.15    50.3  937.78    57.1  932.79
    68.2  922.23    81.5  917.75      99  914.62   109.4  907.28   130.4  895.32
     140     893   157.9  885.42   178.3  880.33   195.3  872.22   201.5  871.48
   218.1   872.2  225.89  869.74   234.6  868.76   252.1  869.75   261.1   871.5
   279.1  871.86   290.9  876.06   304.2   882.5   324.1  889.48   337.7  898.07
   347.2  907.67   353.9  912.74   383.7  926.26   400.3  938.74   418.7  945.79
#Mann= 3 ,-1,0
       0      .1       0  225.89    .045       0   252.1      .1       0
Bank Sta=225.89,252.1
XS Rating Curve= 0 ,0
Exp/Cntr(USF)=0,0
Exp/Cntr=0.3,0.1

Type RM Length L Ch R = 1 ,3182    ,176.3,179.4,176.7
XS GIS Cut Line= 2
1655556.22868462534803.2940459441655983.67547142534956.396104157
#Sta/Elev= 30
       0  987.68      26  966.19    28.6  965.02    36.3  964.09    42.5  962.22
    63.5  951.55    74.8  946.96    80.9  943.42    92.7  932.86   129.7  914.42
     155  890.32     175  869.94   178.5  867.07  180.63  866.27   185.1  865.66
   192.4  866.27     203  865.97     221  872.79   248.2  879.22   285.2   884.7
   293.5  886.77   303.9  887.82   331.3  894.52   351.9  898.31   359.7  901.51
   373.6  911.17   380.6  914.53   411.9  924.09   436.3  935.18     454  938.56
#Mann= 3 ,-1,0
       0      .1       0  180.63    .045       0   192.4      .1       0
Bank Sta=180.63,192.4
XS Rating Curve= 0 ,0
Exp/Cntr(USF)=0,0
Exp/Cntr=0.3,0.1

Type RM Length L Ch R = 1 ,3003    ,128.4,121.3,107
XS GIS Cut Line= 6
1655487.81618884534936.9195969251655568.17396776534971.548136592
1655636.88544451535001.6097562611655734.85736142535038.168082088
1655825.45199651535027.6100323351655941.85661934535033.783904508
#Sta/Elev= 30
       0  997.17    32.4   969.6    43.1   966.5    68.1  956.99    82.4  947.54
    89.5   940.9   100.3  928.23   118.2  913.33   132.5  898.49   143.2   890.5
     154  884.63   167.9  879.05   182.2  869.22  202.74861.9725   206.7  860.71
   213.8   860.5  221.28861.9694   227.7  866.27   245.2   868.6   259.2  874.68
   266.2  876.64   276.2  877.64   302.6  884.01   322.4  886.63   378.5  897.05
   415.8   913.8   437.6  919.64   450.8  921.53   460.6  925.56   474.8  929.75
#Mann= 3 ,-1,0
       0      .1       0  202.74    .045       0  221.28      .1       0
Bank Sta=202.74,221.28
XS Rating Curve= 0 ,0
Exp/Cntr(USF)=0,0
Exp/Cntr=0.3,0.1

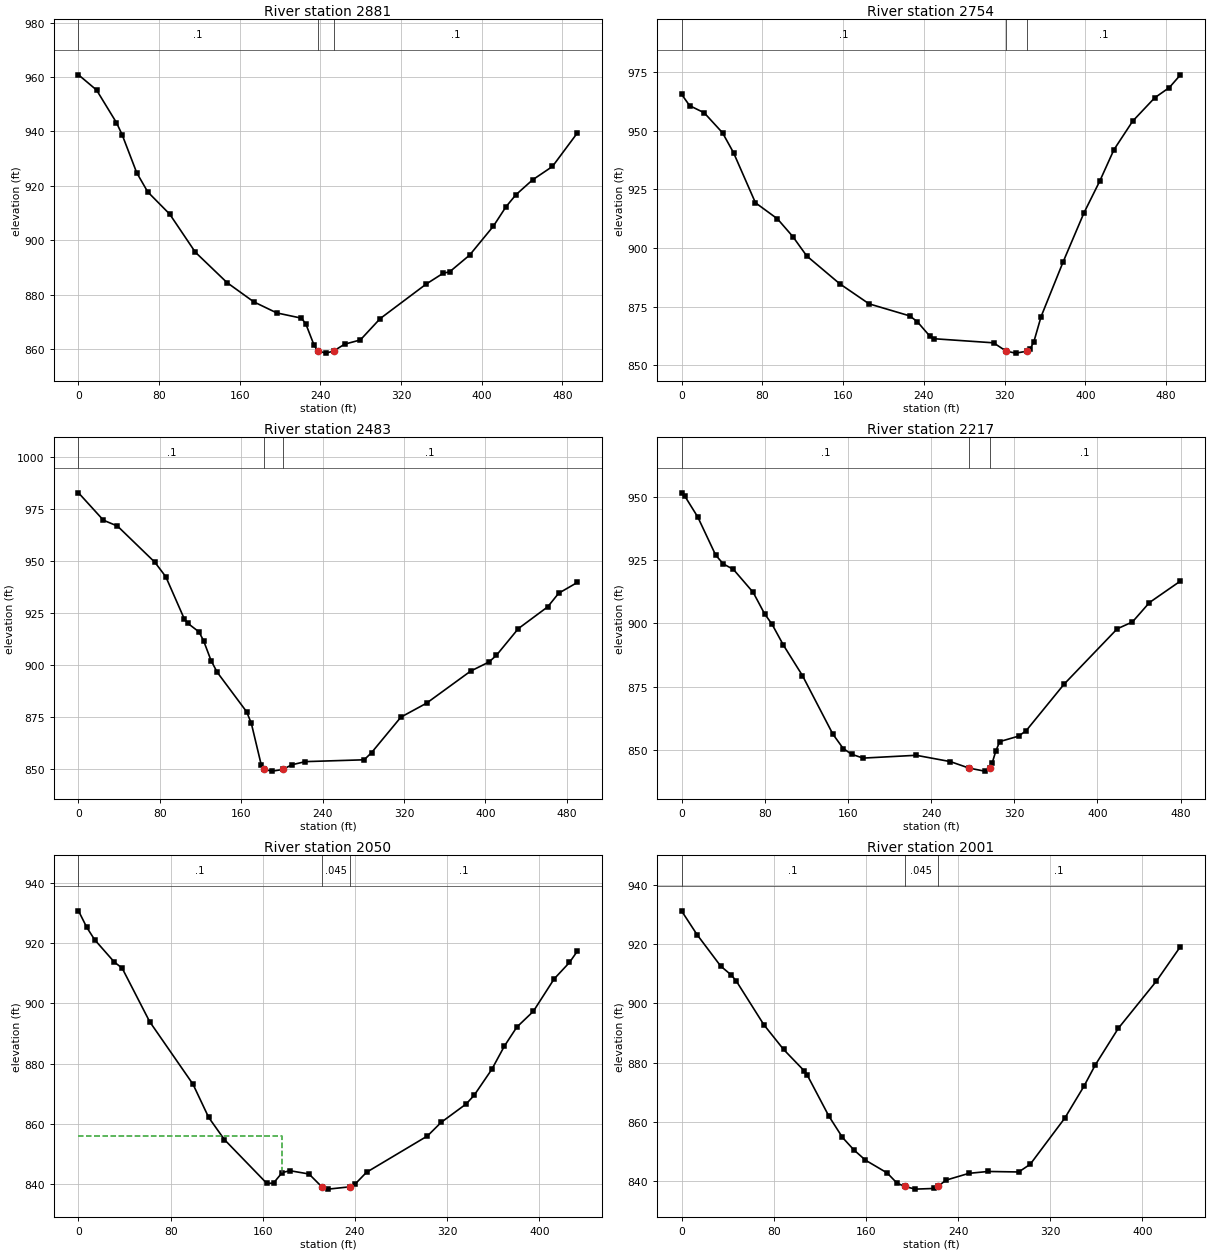
Type RM Length L Ch R = 1 ,2881    ,108.1,127.8,134.6
XS GIS Cut Line= 4
1655494.83779444535046.1230572791655689.97654494535138.515282005
1655742.54453487535075.5929910281655939.27625476535087.540261467
#Sta/Elev= 30
       0  960.82    17.9  955.24    37.7  943.21    43.3   938.8    57.8  924.78
    68.7  917.76    90.5  909.58   115.9  895.59   147.4  884.39   173.9  877.32
   196.7  873.25   221.2  871.32   225.5  869.23   233.8  861.31  237.41  859.24
   245.5  858.46  253.14  859.23     264  861.75   279.6   863.3   299.3  871.16
   345.1   883.9   361.7  887.82   368.3  888.39     388   894.5   411.6  905.15
   424.2  912.34     434  916.72   450.5  922.19   470.2  927.11     495  939.48
#Mann= 3 ,-1,0
       0      .1       0  237.41    .045       0  253.14      .1       0
Bank Sta=237.41,253.14
XS Rating Curve= 0 ,0
Exp/Cntr(USF)=0,0
Exp/Cntr=0.3,0.1

Type RM Length L Ch R = 1 ,2754    ,264.4,270.4,266.1
XS GIS Cut Line= 2
1655480.81635791535053.9889696961655927.73277061535264.614922614
#Sta/Elev= 30
       0  965.47       8   960.6    22.5  957.53    40.6  949.03    51.5  940.55
    73.2  919.22      95  912.36   110.2  904.83     124  896.56   156.7   884.7
   185.7  876.16   226.1  871.01   233.5  868.53   245.8  862.45   250.2  861.29
     309  859.55  321.53 856.001   330.8  855.16  342.53856.0031   345.3  856.96
   348.9     860   356.1  870.75   377.9  894.03   398.6  914.97   414.2  928.47
   428.2  941.81   446.8     954   468.6  963.94   483.1  968.31   494.1  973.72
#Mann= 3 ,-1,0
       0      .1       0  321.53    .045       0  342.53      .1       0
Bank Sta=321.53,342.53
XS Rating Curve= 0 ,0
Exp/Cntr(USF)=0,0
Exp/Cntr=0.3,0.1

Type RM Length L Ch R = 1 ,2483    ,251.7,266.2,266.6
XS GIS Cut Line= 2
1655370.57042068535197.2170941761655816.33963321 535401.52798325
#Sta/Elev= 30
       0  982.85    24.5  969.68    38.3  966.87    75.1  949.44    85.8  942.51
   103.9  922.33   107.5  920.07   118.4  915.99   122.9  911.79   130.3  902.18
   136.4  896.52   165.3  877.53   169.9  871.95   179.7  851.84  182.39849.8077
   190.5  849.01  200.87 849.807   209.5  852.04     223  853.58   280.8  854.46
     288  857.88   316.9  874.98   342.1  881.69   385.4   897.1   403.5   901.5
   410.7  904.68   432.3  917.54   461.2  928.03     472  934.58   490.4  939.77
#Mann= 3 ,-1,0
       0      .1       0  182.39    .045       0  200.87      .1       0
Bank Sta=182.39,200.87
XS Rating Curve= 0 ,0
Exp/Cntr(USF)=0,0
Exp/Cntr=0.3,0.1

Type RM Length L Ch R = 1 ,2217    ,160.8,166.9,166.1
XS GIS Cut Line= 2
1655394.60699587535256.2159605391655604.38074294535687.781742273
#Sta/Elev= 30
       0  951.51     3.2  950.19    15.6  941.99    32.8  926.97    40.1  923.47
    49.9  921.29    68.9  912.23    79.8  903.83    87.1  899.61      98  891.39
   116.3  879.38   145.5  856.31   155.5   850.6   163.7  848.32   174.6  846.82
   225.7  847.93   258.5  845.44  276.46842.8807   291.4  841.68  296.21842.8769
   298.7  844.81   302.3   849.7     306  853.33   324.2   855.5   331.5  857.68
     368  876.05     419  897.85   433.6  900.55     450  908.22   479.8   916.7
#Mann= 3 ,-1,0
       0      .1       0  276.46    .045       0  296.21      .1       0
Bank Sta=276.46,296.21
XS Rating Curve= 0 ,0
Exp/Cntr(USF)=0,0
Exp/Cntr=0.3,0.1

Type RM Length L Ch R = 1 ,2050    ,51.1,48.9,49.7
XS GIS Cut Line= 3
1655311.25092517535314.4801935111655349.31511269535447.290839807
1655397.37969968535738.320549925
#Sta/Elev= 30
       0  930.69     7.2  925.19      14  921.12    31.1  913.69    37.9  911.68
    61.8  893.92    99.4  873.18     113  862.17   126.7   854.8   163.5  840.29
   169.3   840.4   176.8  843.87   183.5   844.5   200.1  843.41  211.21839.1542
   216.7  838.39  235.56839.1544     240  840.02     250  843.97   302.9  856.02
   314.8  860.53   336.5  866.63   343.4  869.49   358.7  878.07   369.7  885.83
   380.5  892.13   394.8  897.35   412.9  908.12   426.2  913.57   433.1  917.35
#Mann= 3 ,-1,0
       0      .1       0  211.21    .045       0  235.56      .1       0
#XS Ineff= 2 , 0
          176.94  855.94
Permanent Ineff=
       F       F
Bank Sta=211.21,235.56
XS Rating Curve= 0 ,0
Exp/Cntr(USF)=0,0
Exp/Cntr=0.3,0.1

Type RM Length L Ch R = 1 ,2001    ,110.7,110,105.9
XS GIS Cut Line= 3
1655263.99355957535321.5752799541655302.05774709 535454.38592625
1655350.12233408535745.415636368
#Sta/Elev= 30
       0  931.17    13.5  923.14      34  912.55    43.1  909.57    47.6  907.48
    71.5  892.78    88.6  884.47   106.7  877.18   109.1  875.86   127.9  862.01
   139.7  854.83   149.7  850.59   159.7  847.16   178.5  842.86   187.1  839.42
  193.79838.3077   202.9  837.41   219.5  837.64  222.61838.3081   229.5  840.43
   249.5  842.73   266.1  843.36   292.7  843.19   302.7  845.79   332.7  861.34
   349.2  871.99   359.2  879.27   379.1  891.56   412.2  907.48   433.1  919.14
#Mann= 3 ,-1,0
       0      .1       0  193.79    .045       0  222.61      .1       0
Bank Sta=193.79,222.61
XS Rating Curve= 0 ,0
Exp/Cntr(USF)=0,0
Exp/Cntr=0.3,0.1

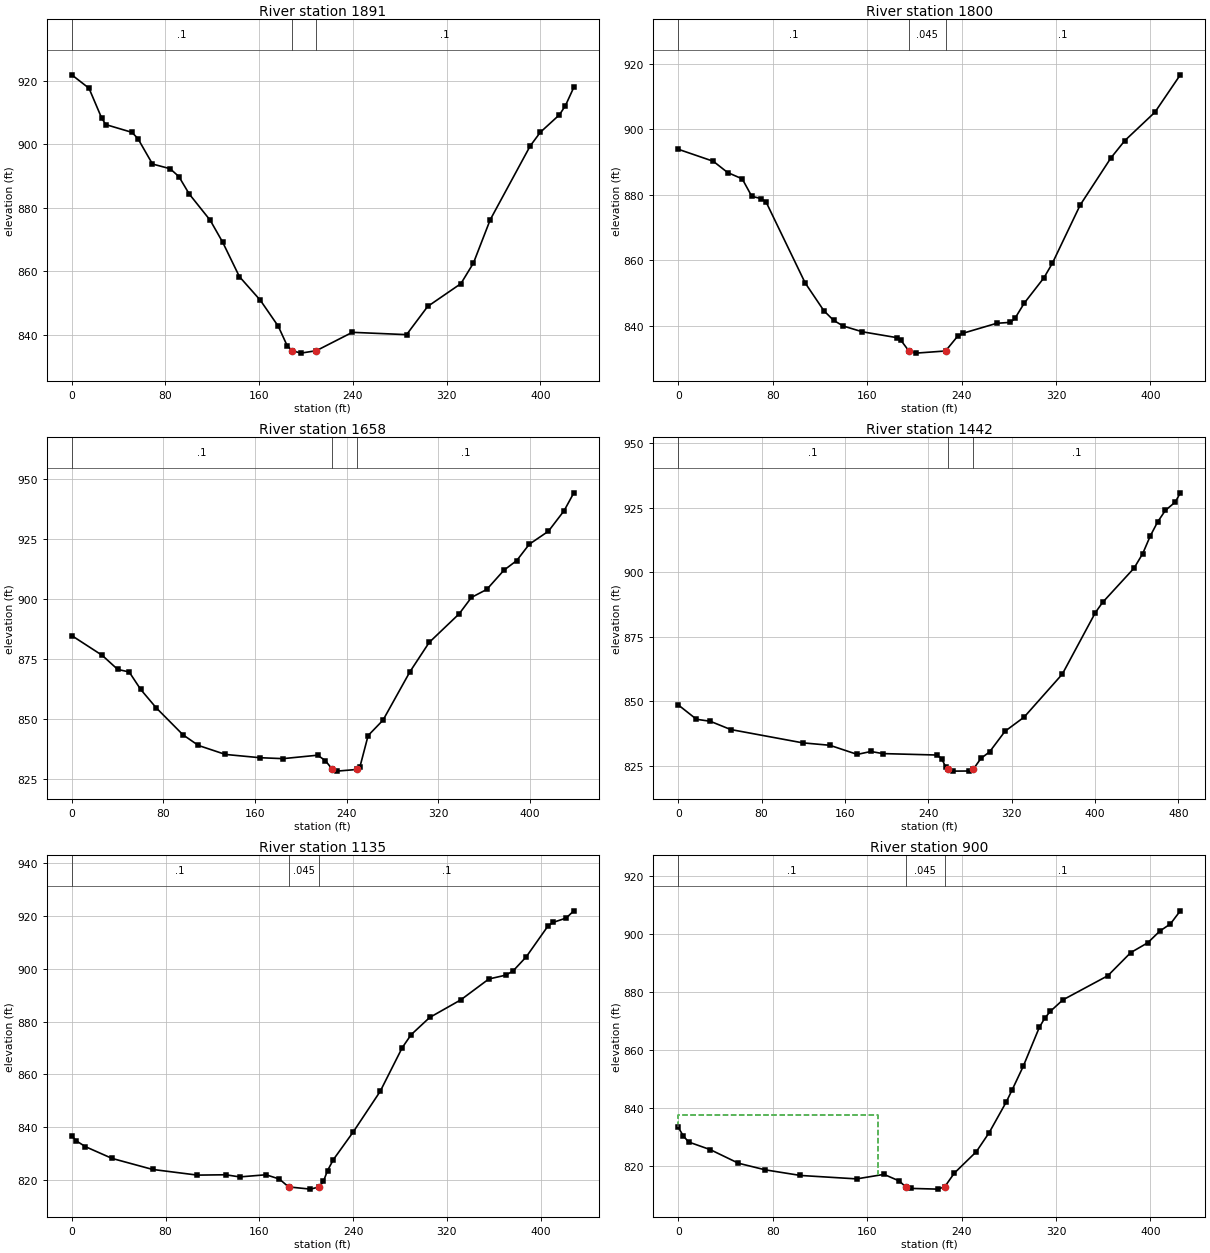
Type RM Length L Ch R = 1 ,1891    ,92.8,91.6,87.8
XS GIS Cut Line= 2
1655129.02033846 535353.828989851655297.40516802535748.017230702
#Sta/Elev= 30
       0  921.88    14.7  917.66    25.4  908.37      29  906.22    51.4  903.77
    56.4  901.83    68.9   893.8    83.9  892.33    91.4  889.87   100.3  884.35
   118.2  876.08   128.8   869.2   143.1  858.35     161   850.9   176.3  842.72
   183.8  836.67  187.98  835.06   195.6  834.27   208.8  835.04   239.5  840.82
   285.8  840.09   303.8  848.96   332.2  856.15   342.9  862.64   357.2  876.25
   391.3  899.47     400   903.8   416.3   909.3   421.4  912.17   428.6  917.97
#Mann= 3 ,-1,0
       0      .1       0  187.98    .045       0   208.8      .1       0
Bank Sta=187.98,208.8
XS Rating Curve= 0 ,0
Exp/Cntr(USF)=0,0
Exp/Cntr=0.3,0.1

Type RM Length L Ch R = 1 ,1800    ,133.4,141.8,142.6
XS GIS Cut Line= 6
1655007.31419709535415.581697345 1655059.1740015535486.057278171
1655103.62470001 535546.465293841655162.45955609535627.327993006
1655204.25179534535689.6923695951655253.26810151535762.419914424
#Sta/Elev= 30
       0  893.96    29.7  890.29    41.8  886.86    54.2  884.92    62.3  879.59
    70.5  878.88    74.5  877.79   107.5  853.16   123.4  844.65   131.6  841.73
   139.7     840     156  838.23     185  836.46   188.5   835.7  195.38832.3759
   201.4  831.72  226.44832.3759   236.6  836.85   241.3   837.8   269.8  840.83
   281.4  841.11   285.2  842.31   293.1  846.98   309.8  854.73   316.9  859.14
   340.5  876.94   366.5  891.31   378.3   896.6   403.8  905.27   425.3  916.68
#Mann= 3 ,-1,0
       0      .1       0  195.38    .045       0  226.44      .1       0
Bank Sta=195.38,226.44
XS Rating Curve= 0 ,0
Exp/Cntr(USF)=0,0
Exp/Cntr=0.3,0.1

Type RM Length L Ch R = 1 ,1658    ,218.9,215.9,212.5
XS GIS Cut Line= 2
1654970.13200381535433.1943501031655063.05521834535861.526119902
#Sta/Elev= 30
       0  884.72    26.6  876.51    40.1  870.66    50.1  869.62    60.2  862.32
    73.6  854.76    97.1  843.47   110.6  839.05   134.1  835.32   164.3  833.96
   184.4  833.57   214.6     835   221.3  832.79  227.56829.0808   231.4  828.38
  249.22829.0811   251.6  830.22   258.7  843.16   271.7  849.57   295.2  869.69
     312  881.88   338.2  893.79   348.9   900.6   362.3  903.93   377.3  911.93
   388.4  915.91   399.4  922.72   416.1  928.12   429.8  936.66   438.3  944.09
#Mann= 3 ,-1,0
       0      .1       0  227.56    .045       0  249.22      .1       0
Bank Sta=227.56,249.22
XS Rating Curve= 0 ,0
Exp/Cntr(USF)=0,0
Exp/Cntr=0.3,0.1

Type RM Length L Ch R = 1 ,1442    ,305.1,307.5,306.4
XS GIS Cut Line= 3
1654789.79482376535474.5015778841654785.01906419535659.609622048
1654931.01448931535917.776243886
#Sta/Elev= 30
       0   848.5    17.5  842.92    30.7  842.15    50.3  838.95   119.3  833.79
   145.5  832.84   171.8   829.3   184.9  830.44   196.2  829.62   248.2  829.06
   252.7   827.7   256.5  824.58   258.7823.5255     264  822.82   279.1  822.87
   283.1823.5243   290.4  827.73   298.8   830.3   313.6  838.28   331.9  843.75
   368.6  860.45   400.3  884.28   407.2  888.22   437.4  901.51   445.7  907.12
   452.9  913.92     460   919.4   467.5  923.92     477  927.14   481.8  930.71
#Mann= 3 ,-1,0
       0      .1       0   258.7    .045       0   283.1      .1       0
Bank Sta=258.7,283.1
XS Rating Curve= 0 ,0
Exp/Cntr(USF)=0,0
Exp/Cntr=0.3,0.1

Type RM Length L Ch R = 1 ,1135    ,239,234.9,232.2
XS GIS Cut Line= 6
1654482.31822948535731.3175165331654527.05632898535808.593936783
1654564.37908898535875.2922942021654611.44461163535963.572629449
1654648.65483906536028.6909375311654692.06682573 536104.66257037
#Sta/Elev= 30
       0  836.72       4  834.84    11.6  832.69    34.4  828.23      69  824.06
   107.2  821.92   131.3  822.05   143.3  821.24   165.7  822.05   177.1  820.44
  184.91817.4625   203.6  816.62  211.15 817.465   214.7  819.59   218.2  823.64
   223.2  827.81   240.2  838.31   263.1  853.59   281.9  870.12   289.5  875.03
   305.3  881.54   331.8  888.19   355.8   896.1   370.2  897.55   376.4  899.11
   387.7  904.48   406.3  916.18   410.4  917.47   421.7  919.14   428.3  921.88
#Mann= 3 ,-1,0
       0      .1       0  184.91    .045       0  211.15      .1       0
Bank Sta=184.91,211.15
XS Rating Curve= 0 ,0
Exp/Cntr(USF)=0,0
Exp/Cntr=0.3,0.1

Type RM Length L Ch R = 1 ,900     ,298.5,299.8,300.1
XS GIS Cut Line= 6
1654254.00041501535909.7424544251654317.74372584535969.922452167
 1654372.1832495536021.6903932541654441.02497534536094.224368915
1654492.32047643536148.9394825851654552.16484493536212.774328679
#Sta/Elev= 30
       0  833.49     4.2  830.57     8.8  828.42    27.1   825.8      51  821.12
    73.8  818.84   103.5  816.92   151.1  815.74   174.3  817.29   187.1  815.05
  192.56813.0618   196.8  812.47     220  812.22  225.79813.0607   233.9  817.74
   252.5  825.08   263.4  831.65   277.8  842.13   282.8   846.3   292.2   854.4
   305.9  867.85   310.5     871   315.2  873.34   325.8  877.27   363.9  885.58
   383.3  893.53   397.7   896.9     408  900.95   416.9  903.38   425.3  907.89
#Mann= 3 ,-1,0
       0      .1       0  192.56    .045       0  225.79      .1       0
#XS Ineff= 2 , 0
          168.88  837.66
Permanent Ineff=
       F       F
Bank Sta=192.56,225.79
XS Rating Curve= 0 ,0
Exp/Cntr(USF)=0,0
Exp/Cntr=0.3,0.1

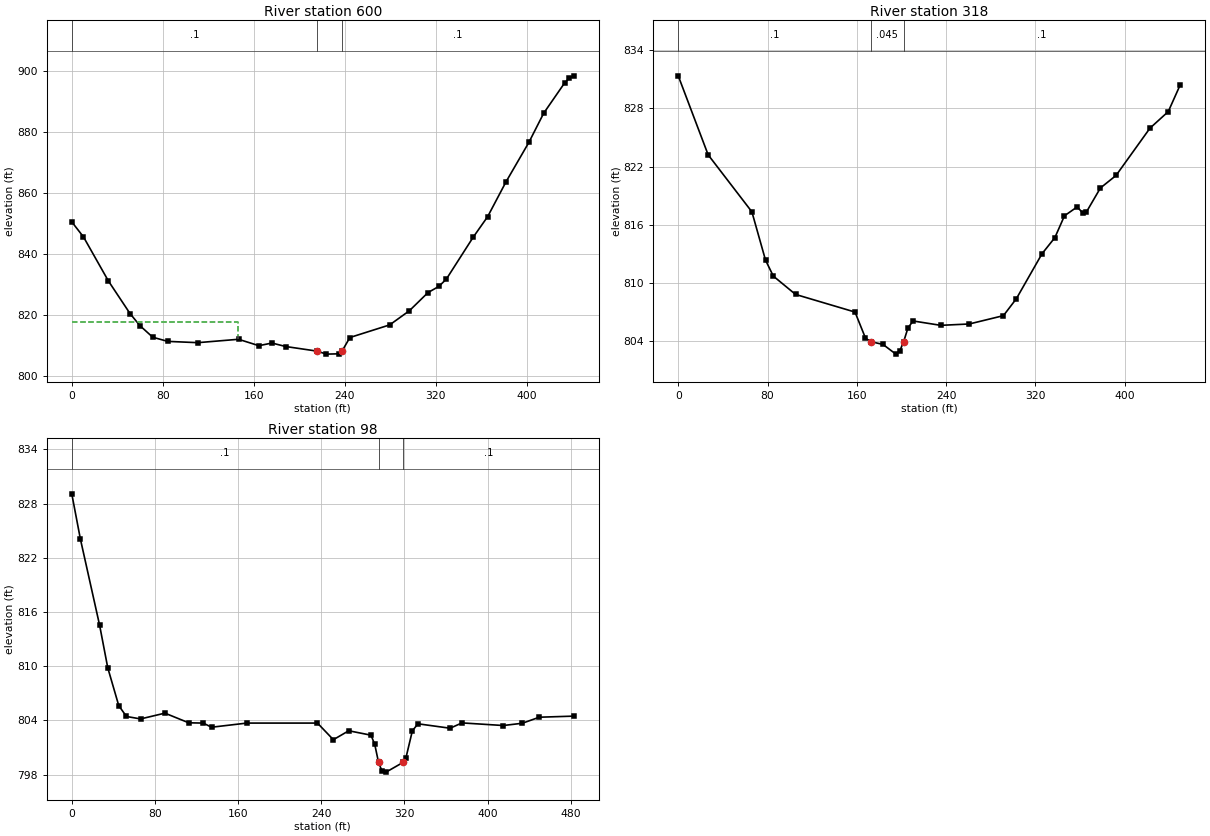
Type RM Length L Ch R = 1 ,600     ,291.7,281.7,276.9
XS GIS Cut Line= 6
1654099.08274584536089.5055463461654143.53246009 536175.92466484
1654185.88769034536245.8087114241654244.26519826536327.000478178
1654287.85927117536388.0298836681654338.71710908536459.231841013
#Sta/Elev= 30
       0  850.59    10.3  845.65    32.2   831.2    51.2  820.52    59.9  816.55
    71.2  812.74    84.4  811.38   110.8  810.96   146.6  812.07   164.5  809.97
     176  810.84     188   809.7  215.65808.1844   223.9   807.2   234.5   807.3
  237.58808.1856   244.5  812.65   279.5  816.79   296.8  821.43   313.2   827.4
   322.6  829.39   329.3   831.8   352.8   845.5   365.6  852.29   381.7  863.68
   401.9  876.69   414.9  886.24   433.2  896.12   437.5   897.8   441.4   898.5
#Mann= 3 ,-1,0
       0      .1       0  215.65    .045       0  237.58      .1       0
#XS Ineff= 2 , 0
          145.85   817.6
Permanent Ineff=
       F       F
Bank Sta=215.65,237.58
XS Rating Curve= 0 ,0
Exp/Cntr(USF)=0,0
Exp/Cntr=0.3,0.1

Type RM Length L Ch R = 1 ,318     ,217.4,219.5,231.5
XS GIS Cut Line= 6
1653820.40014551536303.6032169321653898.87046101536342.315409854
1653966.13082517536375.4974301011654055.81142009536419.739795685
1654128.08489758536463.6311120991654209.48204451536526.483676687
#Sta/Elev= 30
       0  831.36    26.8  823.21      66  817.33    78.2  812.35    85.2   810.7
   105.1  808.81   158.4  806.99   167.8   804.3   172.4803.9406   183.5  803.65
     195  802.65   198.6     803  202.01803.9412   205.9  805.37   210.5  806.07
   235.2  805.62   260.8  805.76   291.4  806.62     303  808.37     326  813.01
   337.5  814.67   346.1  816.92   357.5  817.84   362.4  817.22   365.8  817.32
   378.3  819.79   392.3  821.08   422.7  825.96   439.1  827.67   449.9  830.45
#Mann= 3 ,-1,0
       0      .1       0   172.4    .045       0  202.01      .1       0
Bank Sta=172.4,202.01
XS Rating Curve= 0 ,0
Exp/Cntr(USF)=0,0
Exp/Cntr=0.3,0.1

Type RM Length L Ch R = 1 ,98      ,,,
XS GIS Cut Line= 4
 1653788.6401124536314.719322165 1653889.8486331536509.832655888
1653953.47537628536645.7059110141654003.34391748536747.190196276
#Sta/Elev= 30
       0  829.09     8.3  824.08    26.8  814.53    34.6  809.84    45.2  805.64
    52.6  804.44    66.2  804.17    89.6  804.81   112.5  803.74   126.5  803.71
   134.4  803.25   168.4  803.71   236.3  803.71   251.6  801.87   266.4  802.86
   287.8  802.37   291.4  801.35295.0499 799.361   298.5  798.36   302.3  798.28
318.8699 799.374   321.4  799.86   327.6  802.86     333  803.63   363.9  803.14
   375.3  803.73     415  803.44   433.3  803.69   449.7  804.36   482.9  804.48
#Mann= 3 ,-1,0
       0      .1       0  295.05    .045       0  318.87      .1       0
Bank Sta=295.0499,318.8699
XS Rating Curve= 0 ,0
Exp/Cntr(USF)=0,0
Exp/Cntr=0.3,0.1
LCMann Table=0

Chan Stop Cuts=-1
Use User Specified Reach Order=0
Composite Channel Slope=5